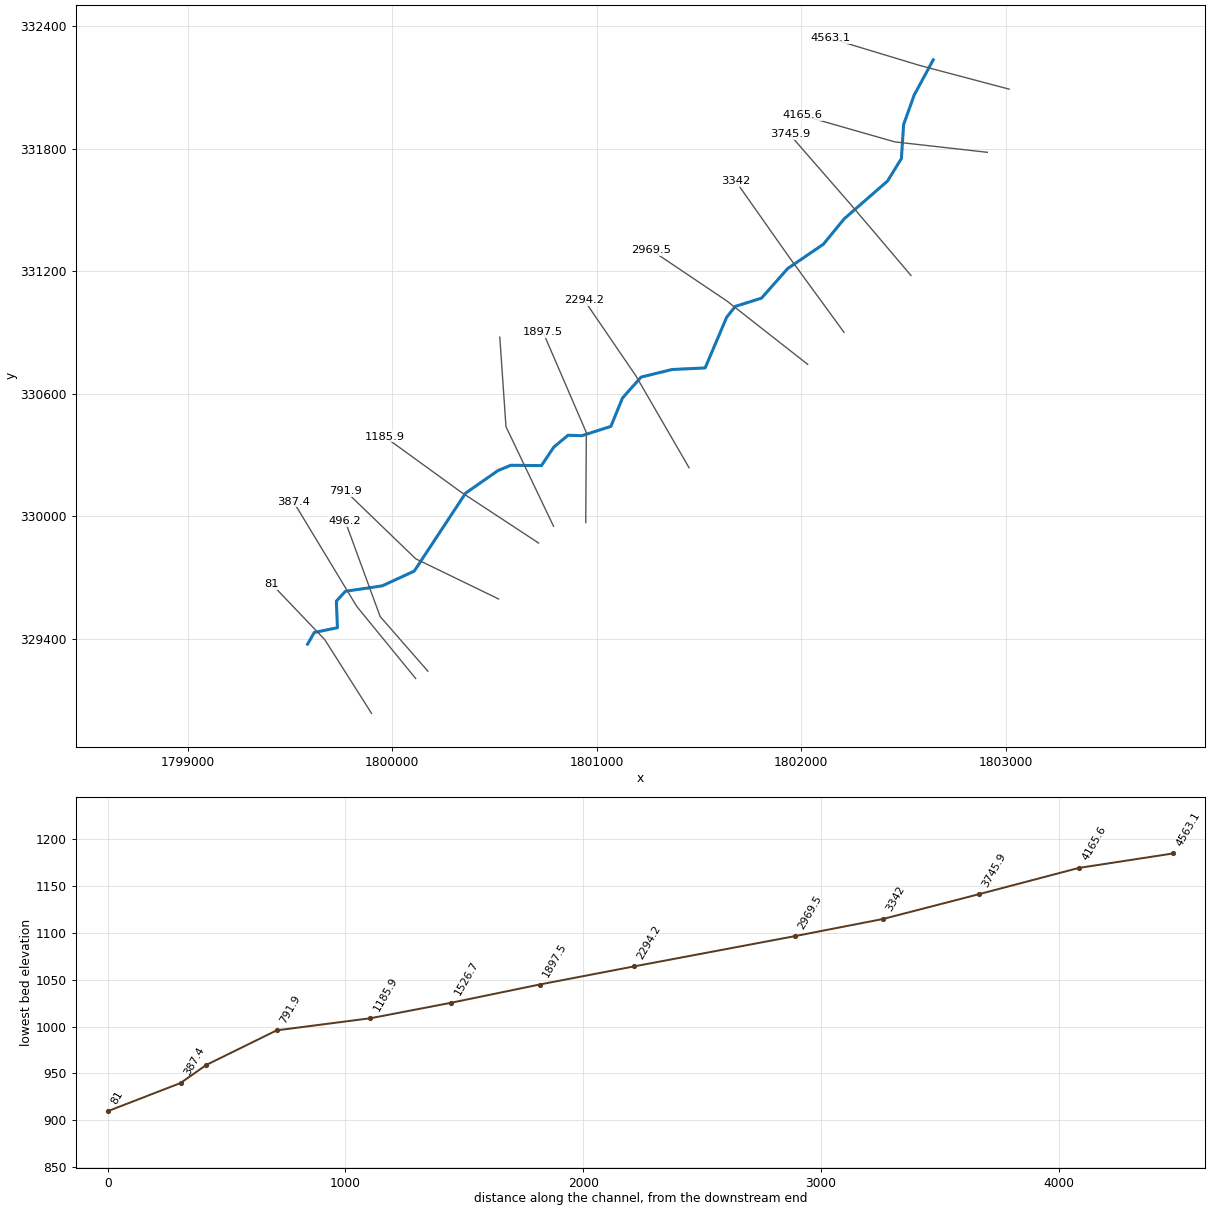
--- BrntCrbnRn.prj (project) ---

Proj Title=BrntCrbnRn
Current Plan=p01
Geom File=g01
Flow File=f01
Plan File=p01
DSS Export Rating Curves=0
DSS Export Rating Curve Sorted=0
DSS Export Volume Flow Curves=0
DXF OffsetX=0
DXF OffsetY=0
DXF ScaleX=0
DXF ScaleY=0

--- BrntCrbnRn.p01 (plan) ---

Plan Title=Floodplain
Program Version=4.00
Geom File=g01
Flow File=f01
K Sum by GR=0
Std Step Tol=0.01
Critical Tol=0.01
Num of Std Step Trials=20
Max Error Tol=0.3
Flow Tol Ratio=0.001
Split Flow NTrial=30
Split Flow Tol=0.02
Split Flow Ratio=0.02
Log Output Level=0
Friction Slope Method=1
Unsteady Friction Slope Method=2
Unsteady Bridges Friction Slope Method=1
Global Log Level=0
CheckData=False
Run HTab=0
Run UNet=0
Run PostProcess=0
UNET Theta=0
UNET Theta Warmup=0
UNET ZTol=0
UNET ZSATol=0
UNET MxIter=0
UNET MaxInSteps=0
UNET DtIC=0
UNET DtMin=0
UNET MaxCRTS=0
UNET WFStab=0
UNET SFStab=0
UNET WFX=0
UNET SFX=0
UNET DSS MLevel=0
UNET DZMax Abort=0
UNET Convert EG Bridges=0
UNET Use Existing IB Tables=0
UNET Froude Limit=0
UNET Froude Power=0
Write IC File=0
Echo Input=False
Echo Output=False
Write Detailed=0

--- BrntCrbnRn.f01 (steady flow) ---

Flow Title=NFF Regression Equation
Program Version=4.00
Number of Profiles=1
Profile Names=P100yr
River Rch & RM=BrntCrbnRn,Main      ,4563.1
     669
River Rch & RM=BrntCrbnRn,Main      ,3745.9
     696
River Rch & RM=BrntCrbnRn,Main      ,387.4
     772
River Rch & RM=BrntCrbnRn,Main      ,81
     776
Boundary for River Rch & Prof#=BrntCrbnRn,Main      ,1
Up Type=0
Dn Type=3
Dn Slope=0.1327

--- BrntCrbnRn.g01 (geometry) ---

Geom Title=USGS 3m DEM
Program Version=4.00

River Reach=BrntCrbnRn     ,Main
Reach XY= 30
     1802645.124      332236.318     1802552.187      332064.112
     1802500.252      331919.240     1802489.318      331752.502
     1802421.495      331642.225     1802209.834      331457.406
     1802107.477      331332.302     1801933.089      331213.359
     1801805.142      331068.352     1801677.118      331028.002
     1801634.832      330974.804     1801529.800      330726.548
     1801367.278      330718.630     1801216.585      330681.667
     1801125.600      330579.310     1801068.735      330439.989
     1800926.572      330394.497     1800858.688      330396.448
     1800789.122      330337.794     1800729.104      330247.766
     1800579.692      330249.490     1800517.141      330223.901
     1800358.082      330112.725     1800107.097      329730.792
     1799950.232      329658.497     1799770.609      329632.055
     1799726.137      329583.625     1799731.573      329453.592
     1799617.962      329429.985     1799585.418      329372.927

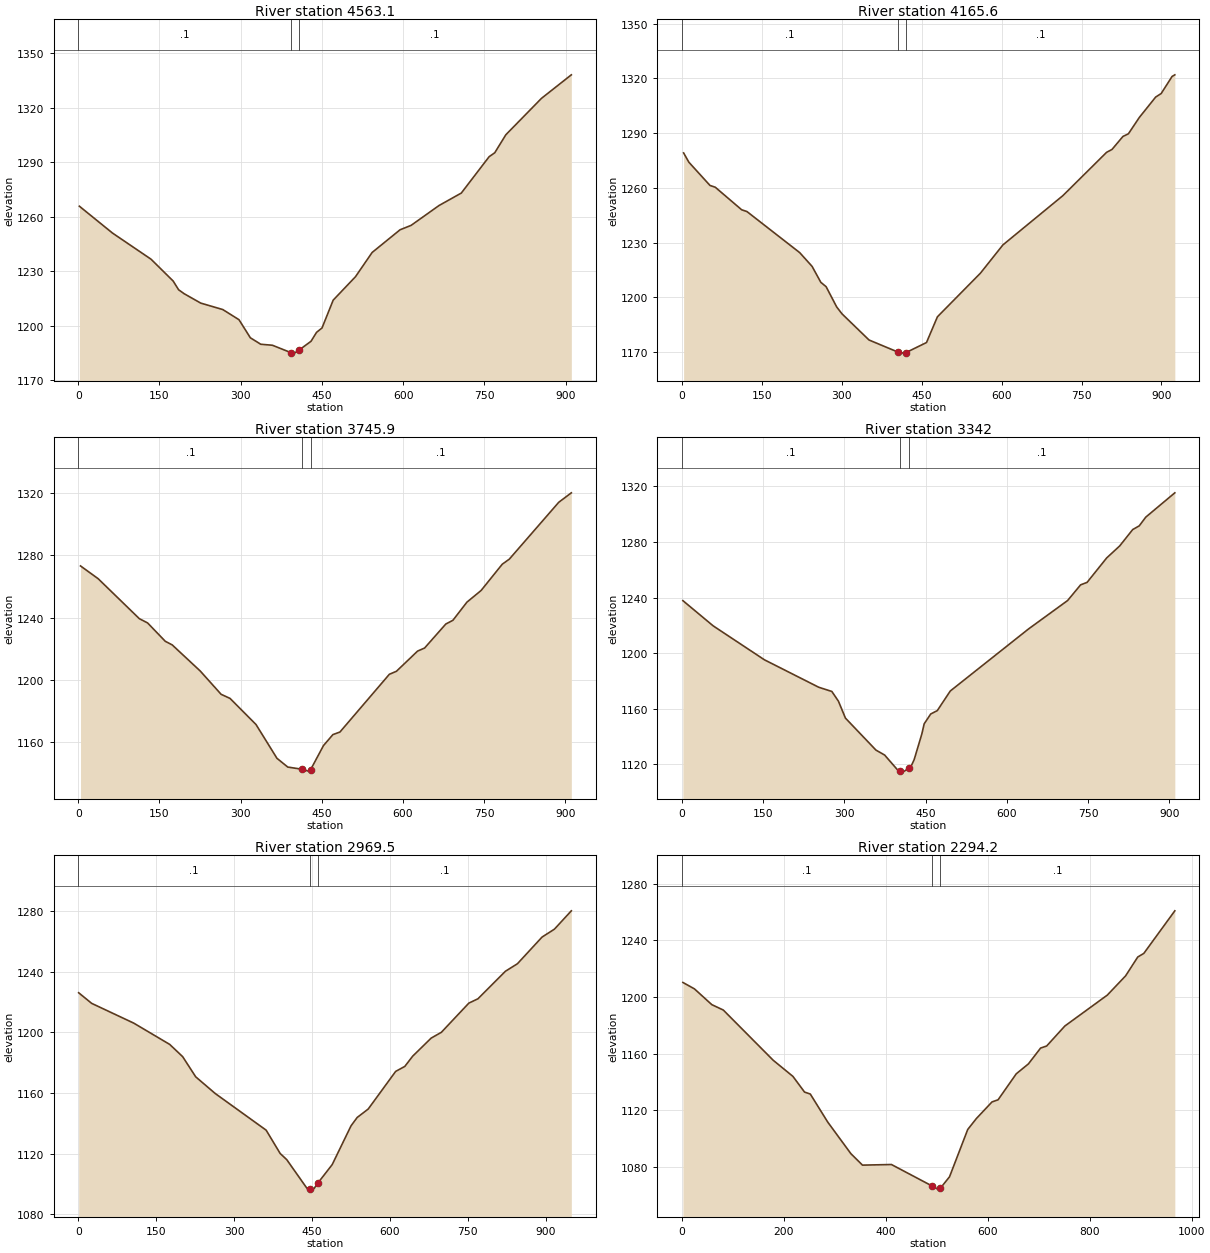
Type RM Length L Ch R = 1 ,4563.1,393.9,397.4,401
XS GIS Cut Line= 3
     1803016.387      332092.609     1802576.687      332209.375
     1802140.971      332341.608
#Sta/Elev= 30
     2.2 1265.72    63.3 1250.95   134.5 1236.55   175.3 1224.54   185.4 1219.73
   195.6 1217.57   226.2 1212.40   266.9 1208.85   296.8 1203.27   317.8 1193.31
   337.0 1189.75   358.5 1189.21   392.4 1185.18   399.2 1184.87   407.4 1186.49
   429.8 1191.39   440.0 1196.31   450.1 1198.72   470.7 1214.03   511.8 1226.90
   542.6 1240.27   594.1 1252.74   614.6 1255.19   666.0 1266.09   707.2 1272.96
   758.6 1292.98   768.9 1295.12   789.4 1305.04   855.2 1325.08   910.3 1338.03
#Mann= 3 , 0 , 0
       0     0.1       0   392.4   0.045       0   407.4     0.1       0
Bank Sta=   392.4,   407.4
Exp/Cntr=0.3,0.1

Type RM Length L Ch R = 1 ,4165.6,436.9,419.7,402.5
XS GIS Cut Line= 3
     1802909.578      331783.099     1802456.996      331834.220
     1802005.669      331963.565
#Sta/Elev= 30
     3.6 1279.16    13.5 1274.05    53.1 1261.33    63.0 1260.35   112.5 1247.99
   122.4 1247.02   221.4 1224.49   244.6 1216.96   261.0 1208.21   270.9 1205.83
   290.7 1194.74   300.6 1190.97   351.4 1176.60   405.2 1170.03   409.6 1169.40
   420.2 1169.63   459.2 1175.21   479.7 1189.32   560.4 1213.25   602.5 1228.72
   715.1 1255.76   797.0 1279.48   807.2 1281.08   827.7 1288.20   837.9 1289.64
   858.4 1298.60   889.1 1309.80   899.4 1311.72   919.8 1321.07   925.0 1321.98
#Mann= 3 , 0 , 0
       0     0.1       0   405.2   0.045       0   420.2     0.1       0
Bank Sta=   405.2,   420.2
Exp/Cntr=0.3,0.1

Type RM Length L Ch R = 1 ,3745.9,405.6,403.9,402.2
XS GIS Cut Line= 3
     1802536.266      331179.514     1802242.341      331526.586
     1801943.171      331870.839
#Sta/Elev= 30
     4.3 1273.21    36.9 1265.00   113.0 1239.31   128.2 1236.60   160.8 1224.82
   173.7 1222.47   225.3 1205.76   264.0 1190.75   280.5 1188.11   328.5 1171.33
   367.1 1149.66   387.1 1144.01   414.3 1142.56   425.1 1141.40   429.3 1142.31
   453.1 1157.82   470.5 1164.86   483.5 1166.52   574.8 1203.62   587.8 1205.52
   626.9 1218.50   639.9 1220.48   679.0 1235.88   692.1 1238.26   718.1 1249.96
   744.2 1257.42   783.3 1274.31   796.4 1277.58   887.6 1314.07   910.9 1320.17
#Mann= 3 , 0 , 0
       0     0.1       0   414.3   0.045       0   429.3     0.1       0
Bank Sta=   414.3,   429.3
Exp/Cntr=0.3,0.1

Type RM Length L Ch R = 1 ,3342,366.2,372.5,378.7
XS GIS Cut Line= 3
     1802208.706      330901.055     1801940.943      331268.907
     1801679.407      331641.326
#Sta/Elev= 30
     2.2 1237.76    58.1 1219.58   152.7 1195.12   252.9 1175.35   277.1 1172.32
   289.3 1165.29   302.2 1153.11   358.5 1130.07   374.5 1126.51   398.8 1115.61
   403.7 1114.93   411.0 1114.91   418.7 1116.91   423.2 1118.29   429.0 1123.16
   443.1 1141.53   447.5 1148.99   459.6 1156.09   471.7 1158.50   495.7 1172.65
   640.0 1217.32   712.2 1237.82   736.2 1249.12   748.2 1250.92   784.3 1268.51
   808.3 1277.15   832.4 1288.98   844.4 1291.63   856.4 1297.89   910.1 1315.44
#Mann= 3 , 0 , 0
       0     0.1       0   403.7   0.045       0   418.7     0.1       0
Bank Sta=   403.7,   418.7
Exp/Cntr=0.3,0.1

Type RM Length L Ch R = 1 ,2969.5,685,675.3,665.8
XS GIS Cut Line= 3
     1802030.972      330744.100     1801635.736      331054.713
     1801265.368      331304.245
#Sta/Elev= 30
     0.9 1226.18    25.9 1219.18   107.0 1206.11   176.1 1192.08   201.1 1183.98
   226.2 1170.67   263.7 1159.67   361.8 1135.44   388.8 1120.05   401.4    1116
   441.5 1096.50   446.2 1096.50   454.0 1096.86   461.2 1100.43   489.0 1112.71
   525.3 1138.35   537.1 1143.83   558.3 1149.39   611.1 1174.23   628.7 1177.52
   643.9 1184.29   679.5 1196.23   699.1 1200.05   752.0 1219.32   769.6 1222.21
   822.4 1240.37   845.6 1245.35   892.9 1262.93   916.8 1268.18   949.3 1280.28
#Mann= 3 , 0 , 0
       0     0.1       0   446.2   0.045       0   461.2     0.1       0
Bank Sta=   446.2,   461.2
Exp/Cntr=0.3,0.1

Type RM Length L Ch R = 1 ,2294.2,410,396.8,389.4
XS GIS Cut Line= 3
     1801450.926      330237.566     1801190.781      330688.099
     1800939.246      331057.303
#Sta/Elev= 30
     2.4 1210.31    25.0 1205.79    59.1 1194.63    81.6 1190.82   179.5 1155.31
   218.1 1143.94   240.9 1132.85   252.2 1131.45   286.3 1111.68   331.8 1089.31
   354.5 1081.21   411.3 1081.64   491.8 1066.32   502.2 1064.25   506.8 1064.70
   525.2 1072.97   560.9 1106.40   577.6 1114.04   608.5 1125.88   620.4 1127.39
   656.1 1145.77   679.9 1152.76   703.8 1163.95   715.7 1165.42   751.4 1179.55
   834.7 1201.41   870.5 1214.99   894.3 1228.31   906.2 1230.86   967.0 1260.95
#Mann= 3 , 0 , 0
       0     0.1       0   491.8   0.045       0   506.8     0.1       0
Bank Sta=   491.8,   506.8
Exp/Cntr=0.3,0.1

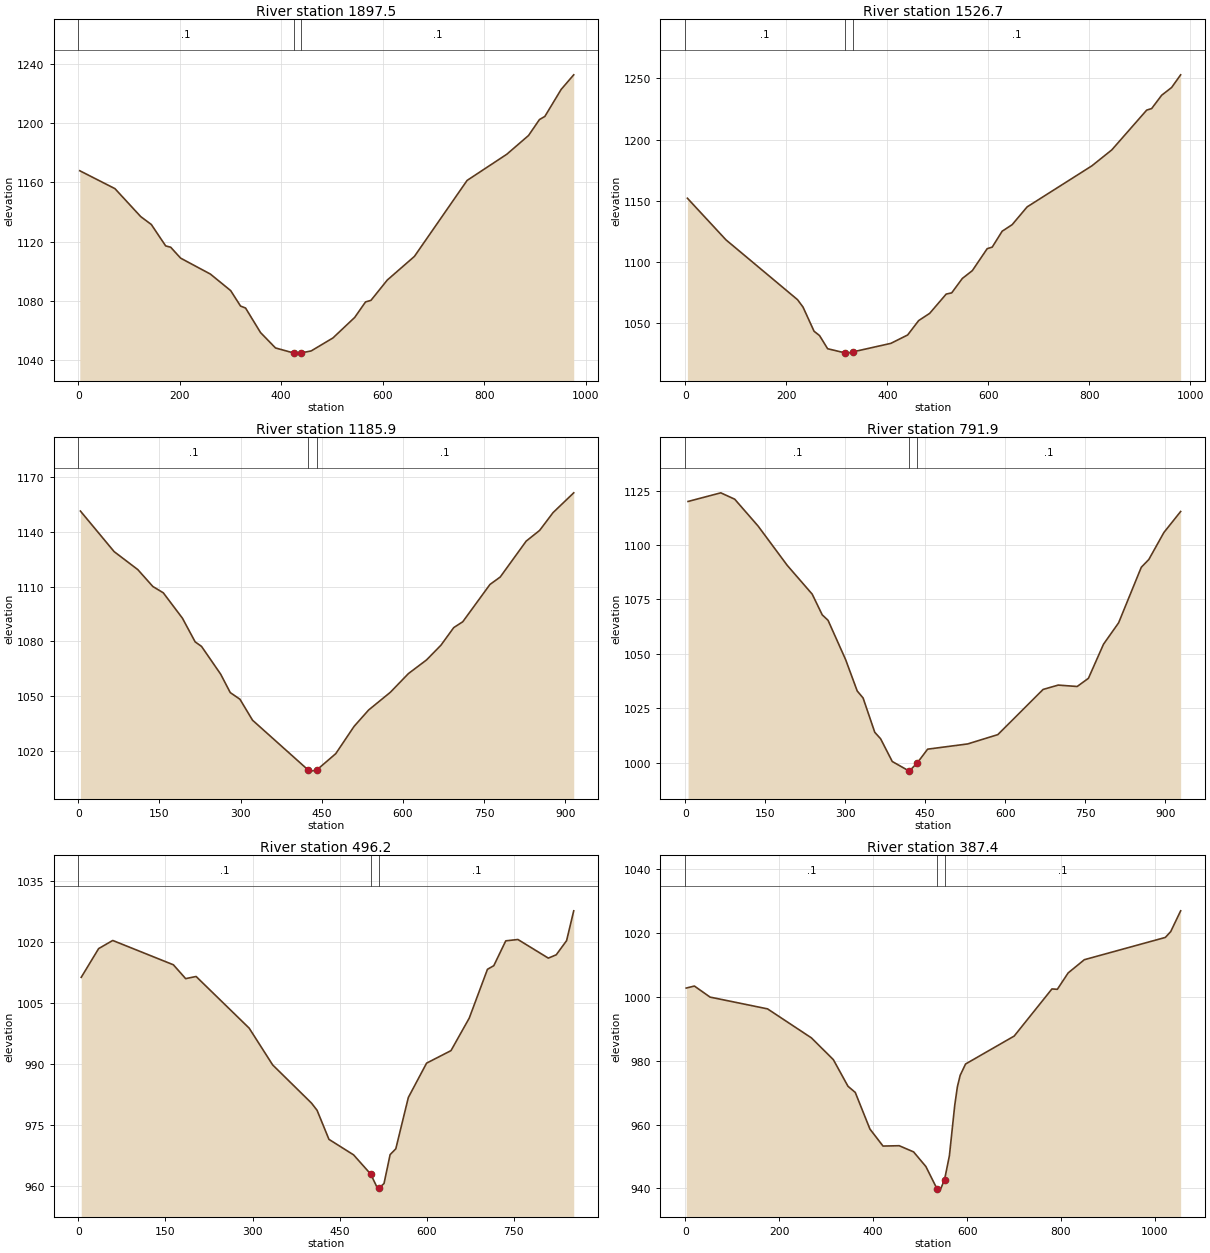
Type RM Length L Ch R = 1 ,1897.5,359.6,370.7,375.8
XS GIS Cut Line= 3
     1800945.770      329968.899     1800948.680      330409.609
     1800736.832      330901.880
#Sta/Elev= 30
     2.9 1167.83    72.2 1155.78   123.0 1136.94   143.9 1131.62   172.2 1117.19
   182.1 1116.30   201.7 1108.94   260.4 1098.20   300.3 1087.08   319.8 1076.66
   329.7 1075.33   359.2 1058.80   388.7 1048.43   424.6 1045.03   428.8 1044.94
   439.6 1045.09   459.1 1046.43   501.9 1055.15   544.8 1068.97   566.2 1079.43
   576.9 1080.50   609.1 1094.19   662.6 1110.12   766.4 1161.30   844.7 1178.95
   887.6 1191.60   909.0 1202.30   919.7 1204.43   951.9 1222.67   976.6 1232.46
#Mann= 3 , 0 , 0
       0     0.1       0   424.6   0.045       0   439.6     0.1       0
Bank Sta=   424.6,   439.6
Exp/Cntr=0.3,0.1

Type RM Length L Ch R = 1 ,1526.7,329.5,340.8,352.1
XS GIS Cut Line= 3
     1800788.470      329950.285     1800555.753      330438.464
     1800525.427      330877.274
#Sta/Elev= 30
     4.3 1152.04    80.6 1118.06   222.3 1069.18   233.2 1063.13   255.0 1043.42
   265.9 1039.86   281.9 1029.12   316.7 1025.69   320.4 1025.53   331.7 1026.53
   407.0 1033.49   440.3 1040.36   462.1 1052.11   483.9 1058.02   516.6 1073.75
   527.5 1074.74   548.5 1086.50   568.3 1092.89   597.8 1110.86   607.7 1112.10
   627.4 1125.10   647.2 1130.45   676.8 1144.96   805.0 1178.49   844.4 1191.50
   913.5 1224.00   923.3 1225.27   943.1 1236.13   962.8 1242.45   980.7 1252.82
#Mann= 3 , 0 , 0
       0     0.1       0   316.7   0.045       0   331.7     0.1       0
Bank Sta=   316.7,   331.7
Exp/Cntr=0.3,0.1

Type RM Length L Ch R = 1 ,1185.9,391.1,394,397
XS GIS Cut Line= 3
     1800715.009      329868.532     1800334.927      330118.859
     1799962.152      330389.522
#Sta/Elev= 30
     3.9 1151.46    66.2 1129.24   110.0 1119.37   137.8 1110.12   157.1 1106.66
   192.5 1092.74   216.0 1079.77   227.8 1077.29   263.2 1062.06   280.9 1051.98
   298.8 1048.34   322.1 1036.84   425.4 1009.44   428.1 1008.95   440.4 1009.47
   475.9 1018.52   509.8 1033.47   536.7 1042.45   576.7 1052.12   610.2 1062.39
   643.7 1069.88   670.4 1077.97   694.0 1087.60   710.7 1090.80   761.0 1111.25
   779.9 1115.31   828.0 1135.01   852.8 1140.86   877.6 1150.61   915.8 1161.45
#Mann= 3 , 0 , 0
       0     0.1       0   425.4   0.045       0   440.4     0.1       0
Bank Sta=   425.4,   440.4
Exp/Cntr=0.3,0.1

Type RM Length L Ch R = 1 ,791.9,313.1,295.7,278.1
XS GIS Cut Line= 3
     1800519.679      329594.305     1800114.060      329791.338
     1799770.432      330123.596
#Sta/Elev= 30
     5.3 1120.04    66.7 1124.01    92.8 1121.08   136.6 1108.74   191.3 1090.65
   238.1 1077.41   256.9 1067.89   267.8 1065.39   300.7 1047.34   322.5 1032.88
   333.5 1029.67   355.4 1013.89   366.3 1010.94   388.2 1000.46   420.1  996.04
   420.4  996.11   435.4  999.93   454.5 1006.14   529.5 1008.54   586.1 1012.82
   671.0 1033.60   699.3 1035.60   734.9 1034.96   756.0 1038.72   784.3 1054.41
   812.6 1064.24   855.1 1089.78   869.2 1093.34   897.5 1105.77   928.9 1115.42
#Mann= 3 , 0 , 0
       0     0.1       0   420.4   0.045       0   435.4     0.1       0
Bank Sta=   420.4,   435.4
Exp/Cntr=0.3,0.1

Type RM Length L Ch R = 1 ,496.2,104.3,108.9,113.5
XS GIS Cut Line= 3
     1800173.819      329240.331     1799940.274      329508.475
     1799769.441      329975.564
#Sta/Elev= 30
     5.0 1011.32    35.0 1018.40    59.3 1020.40   163.7 1014.41   184.8 1011.00
   202.8 1011.53   294.2  998.80   334.6  989.75   401.5  980.34   411.1  978.56
   431.5  971.42   473.9  967.60   503.4  962.86   515.8  959.16   518.4  959.51
   526.3  960.54   536.8  967.66   546.6  969.09   568.2  981.74   599.6  990.19
   641.6  993.27   673.0 1001.27   704.4 1013.30   715.3 1014.19   735.9 1020.31
   756.8 1020.64   809.2 1016.05   822.8 1016.87   840.6 1020.35   852.9 1027.70
#Mann= 3 , 0 , 0
       0     0.1       0   503.4   0.045       0   518.4     0.1       0
Bank Sta=   503.4,   518.4
Exp/Cntr=0.3,0.1

Type RM Length L Ch R = 1 ,387.4,302.6,306.4,305.7
XS GIS Cut Line= 3
     1800113.981      329204.694     1799825.664      329558.211
     1799516.434      330070.712
#Sta/Elev= 30
     2.1 1002.73    19.5 1003.36    52.9  999.90   175.2  996.22   268.6  987.14
   315.3  980.33   346.5  971.99   362.0  970.06   393.2  958.60   421.1  953.27
   455.5  953.38   486.2  951.44   512.4  946.85   536.4  939.79     537  939.84
   543.6  939.79     552  942.70   562.4  950.24   573.8  966.07   579.4  971.83
   585.3  975.40   596.8  978.96   700.3  987.70   780.7 1002.46   792.2 1002.34
   815.2 1007.47   849.7 1011.61  1022.1 1018.58  1033.5 1020.39  1054.7 1026.91
#Mann= 3 , 0 , 0
       0     0.1       0     537   0.045       0     552     0.1       0
Bank Sta=     537,     552
Exp/Cntr=0.3,0.1

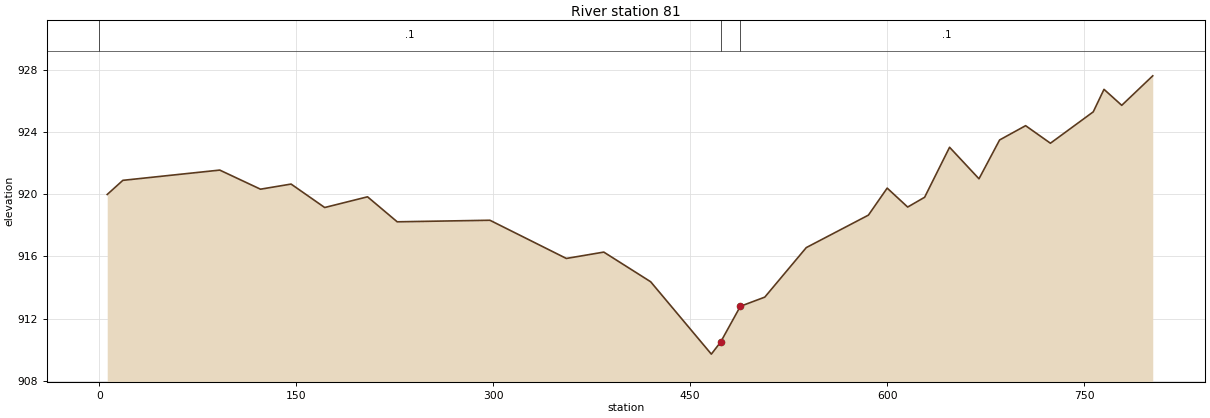
Type RM Length L Ch R = 1 ,81,74.6,81,87.4
XS GIS Cut Line= 3
     1799898.279      329033.699     1799669.708      329394.750
     1799411.106      329666.198
#Sta/Elev= 30
     6.1  919.99    18.0  920.90    91.8  921.56   122.8  920.33   146.1  920.66
   171.7  919.15   204.3  919.84   226.9  918.23   297.5  918.33   355.7  915.87
   384.2  916.28   419.9  914.37   466.1  909.71   473.2  910.49   488.2  912.79
   506.8  913.38   538.4  916.57   585.7  918.66   600.0  920.40   615.6  919.18
   628.5  919.81   647.5  923.03   669.9  921.00   685.6  923.50   705.4  924.42
   724.3  923.29   756.9  925.31   765.1  926.76   778.6  925.73   802.2  927.63
#Mann= 3 , 0 , 0
       0     0.1       0   473.2   0.045       0   488.2     0.1       0
Bank Sta=   473.2,   488.2
Exp/Cntr=0.3,0.1